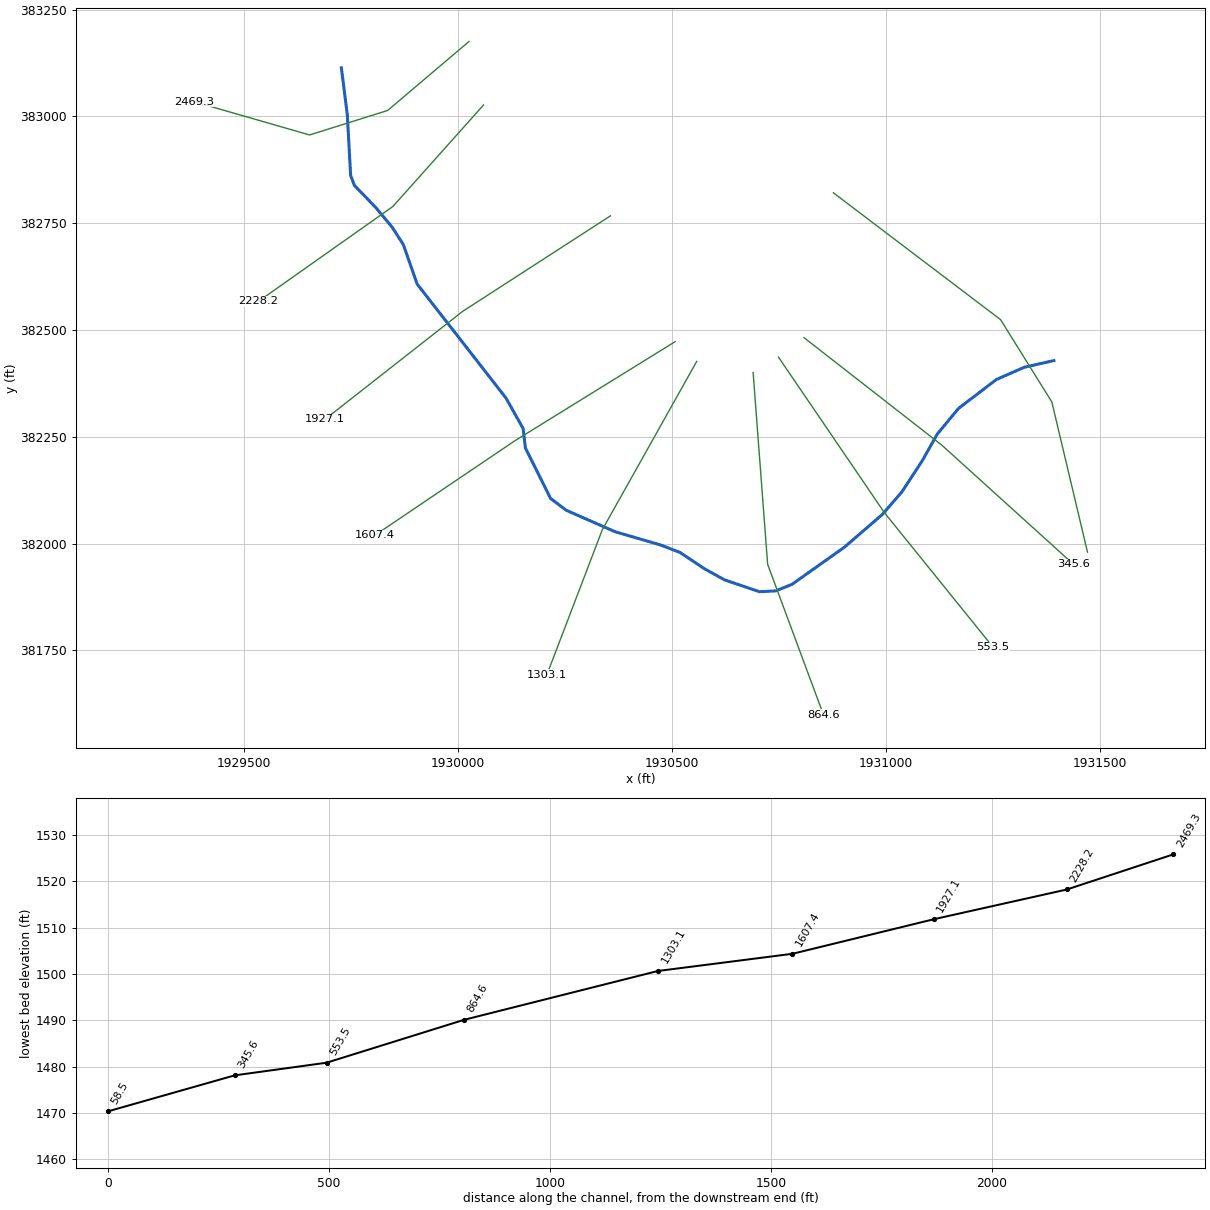
--- FICKEYRN.prj (project) ---

Proj Title=FICKEYRN
Current Plan=p01
Default Exp/Contr=0,0
English Units
Geom File=g01
Flow File=f01
Plan File=p01
BEGIN DESCRIPTION:
END DESCRIPTION:
DSS Export Rating Curves= 0
DSS Export Rating Curve Sorted= 0
DSS Export Volume Flow Curves= 0
DXF OffsetX= 0
DXF OffsetY= 0
DXF ScaleX= 0
DXF ScaleY= 0

--- FICKEYRN.p01 (plan) ---

Plan Title=Floodplain
Program Version=4.00
Geom File=g01
Flow File=f01
K Sum by GR=0
Std Step Tol=0.01
Critical Tol=0.01
Num of Std Step Trials=20
Max Error Tol=0.3
Flow Tol Ratio=0.001
Split Flow NTrial=30
Split Flow Tol=0.02
Split Flow Ratio=0.02
Log Output Level=0
Friction Slope Method=1
Unsteady Friction Slope Method=2
Unsteady Bridges Friction Slope Method=1
Global Log Level=0
CheckData=False
Run HTab=0
Run UNet=0
Run PostProcess=0
UNET Theta=0
UNET Theta Warmup=0
UNET ZTol=0
UNET ZSATol=0
UNET MxIter=0
UNET MaxInSteps=0
UNET DtIC=0
UNET DtMin=0
UNET MaxCRTS=0
UNET WFStab=0
UNET SFStab=0
UNET WFX=0
UNET SFX=0
UNET DSS MLevel=0
UNET DZMax Abort=0
UNET Convert EG Bridges=0
UNET Use Existing IB Tables=0
UNET Froude Limit=0
UNET Froude Power=0
Write IC File=0
Echo Input=False
Echo Output=False
Write Detailed=0

--- FICKEYRN.f01 (steady flow) ---

Flow Title=NFF Regression Equation
Program Version=4.00
Number of Profiles=1
Profile Names=P100yr
River Rch & RM=FICKEYRN,Main      ,2469.3
   448.8
River Rch & RM=FICKEYRN,Main      ,2228.2
1428.778
River Rch & RM=FICKEYRN,Main      ,58.5
1446.894
Boundary for River Rch & Prof#=FICKEYRN,Main      ,1
Up Type=0
Dn Type=3
Dn Slope=0.023339

--- FICKEYRN.g01 (geometry) ---

Geom Title=USGS 10m DEM
Program Version=4.10

River Reach=FICKEYRN        ,Main
Reach XY= 30
     1929727.609      383113.629     1929741.498      383004.254
     1929749.311      382861.893     1929757.991      382838.455
      1929807.47       382787.24     1929846.533      382740.365
     1929872.575      382699.566     1929904.693      382607.552
     1930112.441      382340.472     1930152.372      382269.292
      1930157.58      382224.153      1930216.39      382105.773
        1930253.      382078.039     1930367.384      382027.679
     1930473.553      381996.722     1930518.691      381979.361
     1930575.983      381941.167     1930622.858      381915.125
     1930704.455      381887.347     1930742.583      381889.236
     1930780.844      381904.708     1930903.067      381991.514
     1930991.535      382067.956     1931037.609      382121.229
     1931085.031      382193.924     1931120.187      382256.424
     1931169.667       382316.32     1931258.208      382384.028
     1931323.312      382412.674     1931392.659      382428.411

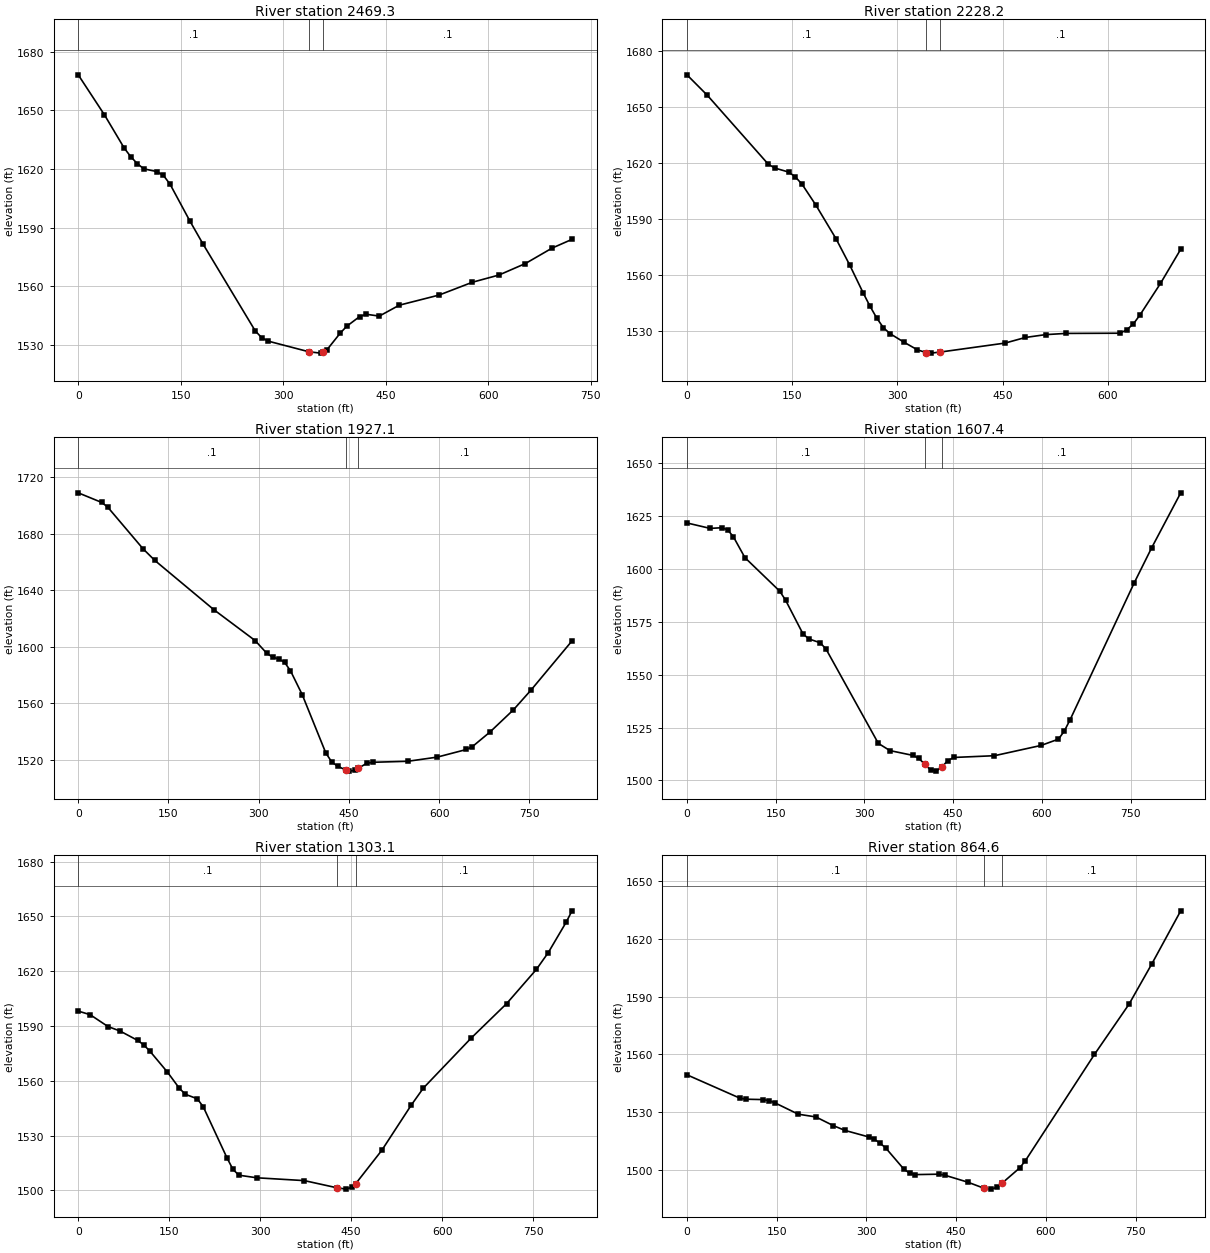
Type RM Length L Ch R = 1 ,2469.3  ,233.4,241.2,248.9
XS GIS Cut Line= 4
      1930025.83      383175.261     1929835.726      383013.802
     1929653.434      382956.511     1929382.601      383034.636
#Sta/Elev= 30
       0 1668.23    38.4 1647.73    67.2 1630.79    76.7  1626.4    86.3 1622.82
    95.9 1620.13   115.1 1618.71   124.7 1616.74   134.3 1612.28   163.1 1593.58
   182.3  1581.8     259 1537.19   268.5 1533.68   278.1 1531.94   337.5 1526.51
   354.5 1525.82   357.5 1526.39   364.1 1527.63   383.2 1536.01   392.7 1539.54
   411.8 1544.56   421.4  1545.7   440.5 1544.78   469.7 1550.35     528 1555.54
   576.6 1562.09   615.5 1565.78   654.3 1571.68   693.2 1579.56   722.4 1584.04
#Mann= 3 , 0 , 0
       0      .1       0   337.5    .045       0   357.5      .1       0
Bank Sta=337.5,357.5
XS Rating Curve= 0 ,0
Exp/Cntr=0.3,0.1

Type RM Length L Ch R = 1 ,2228.2  ,299.7,301,302.3
XS GIS Cut Line= 3
     1930059.973      383026.823     1929847.878      382788.976
     1929533.642      382566.754
#Sta/Elev= 30
       0 1667.02      29  1656.1   115.9 1619.23   125.5 1617.14   144.8 1615.05
   154.5 1612.44   164.2 1608.43   183.5 1597.49   212.4  1579.4   231.8 1565.44
   251.1 1550.43   260.7 1543.41   270.4 1537.01     280 1531.78   289.7 1528.58
     309 1524.13   328.3 1520.01   340.9  1518.5   347.5 1518.23   360.9  1518.8
   453.4 1523.61   482.2  1526.6   511.1 1528.12     540 1528.77     617 1528.88
   626.6 1530.64   636.2 1533.88   645.8 1538.78   674.7 1555.46   703.6 1573.78
#Mann= 3 , 0 , 0
       0      .1       0   340.9    .045       0   360.9      .1       0
Bank Sta=340.9,360.9
XS Rating Curve= 0 ,0
Exp/Cntr=0.3,0.1

Type RM Length L Ch R = 1 ,1927.1  ,321.8,319.8,317.6
XS GIS Cut Line= 3
     1930356.288      382767.068     1930010.836      382543.415
     1929689.121      382290.638
#Sta/Elev= 30
       0 1708.82    39.2 1701.98      49  1698.7   107.8 1669.16   127.4 1660.92
   225.4  1626.1     294 1604.24   313.6 1595.12   323.4 1592.42   333.1 1591.28
   342.9 1588.82   352.7 1582.92   372.3 1565.94   411.5 1524.66   421.3 1518.32
     431 1515.32   445.2 1512.53   450.5 1511.81   460.2 1512.32   465.2 1513.79
   479.7 1517.39   489.5 1518.07   547.9 1518.79   596.6 1521.72   645.3 1527.14
   655.1 1529.15   684.3 1539.47   723.3  1555.2   752.5 1569.16   820.7    1604
#Mann= 3 , 0 , 0
       0      .1       0   445.2    .045       0   465.2      .1       0
Bank Sta=445.2,465.2
XS Rating Curve= 0 ,0
Exp/Cntr=0.3,0.1

Type RM Length L Ch R = 1 ,1607.4  ,292,304.3,318.9
XS GIS Cut Line= 3
     1930507.606      382472.681     1930132.601      382240.365
     1929806.663      382019.886
#Sta/Elev= 30
       0 1621.84    39.2 1619.26    58.8 1619.58    68.6 1618.63    78.4 1615.35
      98 1605.42   156.8 1589.56   166.6 1585.34   196.1 1569.34   205.9 1566.96
   225.5 1565.09   235.3 1562.02   323.5 1517.48   343.1 1514.07   382.3 1511.78
   392.1 1510.35   401.9 1507.61   411.7 1504.95   421.5 1504.35   431.3  1506.5
   441.1 1509.36     451 1510.82   519.8 1511.65   598.5 1516.51     628  1519.5
   637.9 1523.36   647.7 1528.73   755.9 1593.43   785.4 1610.04   834.6  1636.1
#Mann= 3 , 0 , 0
       0      .1       0   401.9    .045       0   431.3      .1       0
Bank Sta=401.9,431.3
XS Rating Curve= 0 ,0
Exp/Cntr=0.3,0.1

Type RM Length L Ch R = 1 ,1303.1  ,416.5,438.5,457.6
XS GIS Cut Line= 3
     1930557.994      382426.443     1930337.429      382032.511
     1930208.121       381693.49
#Sta/Elev= 30
       0 1598.15    19.6  1596.2    49.1 1589.68    68.7 1587.28    98.2 1582.07
     108 1579.63   117.8 1576.35   147.2  1564.7   166.8 1555.86   176.7 1552.58
   196.3 1550.13   206.1 1545.79   245.4  1517.7   255.2 1511.43     265 1508.27
   294.4 1506.85     373  1505.3  426.54 1501.38   441.7 1500.64   451.5 1501.68
   457.6 1503.63   500.5 1521.84   549.5 1546.81   569.2    1556   647.6 1583.24
   706.4 1602.23   755.5 1620.96   775.1 1630.16   804.5 1646.75   814.3 1653.07
#Mann= 3 , 0 , 0
       0      .1       0  426.54    .045       0   457.6      .1       0
Bank Sta=426.54,457.6
XS Rating Curve= 0 ,0
Exp/Cntr=0.3,0.1

Type RM Length L Ch R = 1 ,864.6   ,305.2,311.1,319.1
XS GIS Cut Line= 3
     1930689.812      382400.339     1930723.746      381951.302
     1930853.955       381599.74
#Sta/Elev= 30
       0 1549.43    88.1 1537.36    97.9 1536.77   127.3 1536.56     137 1536.01
   146.8 1534.91     186 1528.99   215.4 1527.57   244.7 1523.04   264.3 1520.55
   303.5 1517.21   313.3 1515.92     323 1513.94   332.8 1511.24   362.2 1500.58
     372  1498.4   381.8 1497.64     421 1497.85   430.7 1497.35   469.5  1493.7
  495.71 1490.64     508  1490.1   517.6 1490.98   527.2 1493.35   556.1  1501.1
   565.7 1504.91     681 1559.99   738.7 1586.03   777.2 1607.15   825.2 1634.52
#Mann= 3 , 0 , 0
       0      .1       0  495.71    .045       0   527.2      .1       0
Bank Sta=495.71,527.2
XS Rating Curve= 0 ,0
Exp/Cntr=0.3,0.1

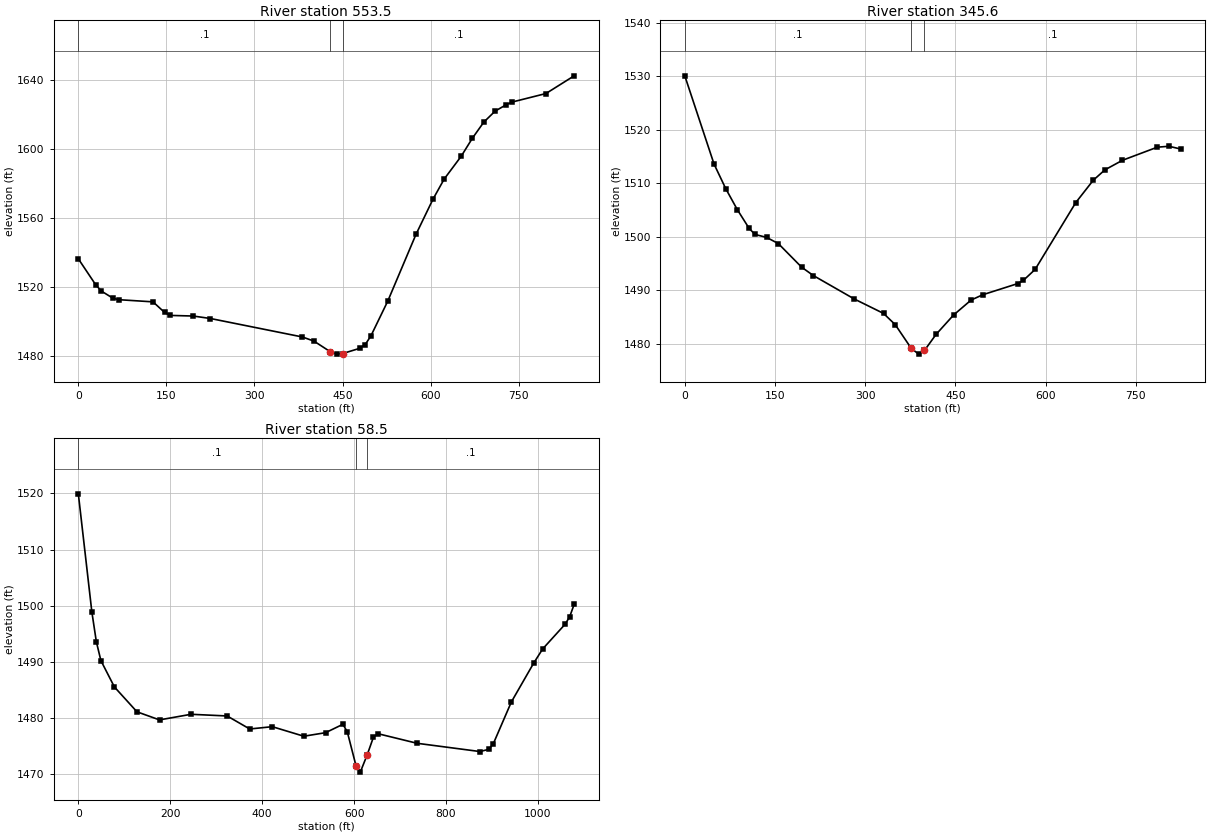
Type RM Length L Ch R = 1 ,553.5   ,199.8,207.9,213.3
XS GIS Cut Line= 3
     1930749.096      382436.387     1930996.733      382072.148
     1931250.368      381757.638
#Sta/Elev= 30
       0 1536.24    29.4 1521.23    39.2 1517.49    58.7 1513.39    68.5 1512.49
   127.2 1511.22   146.8  1505.1   156.6 1503.34   195.8 1502.98   225.1 1501.54
   381.7  1490.8   401.3 1488.41   429.2 1482.22   440.4 1480.84   450.1 1481.17
   478.9 1484.17   488.6  1486.4   498.2 1491.35     527 1511.63   575.1 1550.44
     604 1570.86   623.2 1582.64   652.1 1595.84   671.3  1606.4   690.6 1615.68
   709.8 1622.06     729 1625.84   738.7 1627.34   796.4 1632.29   844.5 1642.59
#Mann= 3 , 0 , 0
       0      .1       0   429.2    .045       0   450.1      .1       0
Bank Sta=429.2,450.1
XS Rating Curve= 0 ,0
Exp/Cntr=0.3,0.1

Type RM Length L Ch R = 1 ,345.6   ,295.6,287.1,278.8
XS GIS Cut Line= 3
      1930808.61      382482.091     1931130.366      382230.721
     1931438.793      381951.166
#Sta/Elev= 30
       0 1530.06    48.6  1513.6      68 1509.02    87.5 1505.05   106.9  1501.6
   116.7 1500.45   136.1  1499.9   155.6 1498.74   194.4 1494.33   213.9 1492.77
   281.9  1488.4   330.5 1485.71     350 1483.61   376.6 1479.19   388.9 1478.11
   398.6  1478.8     418 1481.81     447 1485.41   476.1  1488.2   495.4 1489.19
   553.5 1491.27   563.2 1491.89   582.6 1493.92   650.3 1506.41   679.4 1510.58
   698.7 1512.51   727.8 1514.29   785.8 1516.74   805.2 1516.91   824.6  1516.4
#Mann= 3 , 0 , 0
       0      .1       0   376.6    .045       0   398.6      .1       0
Bank Sta=376.6,398.6
XS Rating Curve= 0 ,0
Exp/Cntr=0.3,0.1

Type RM Length L Ch R = 1 ,58.5    ,67.1,58.5,49.8
XS GIS Cut Line= 4
     1930877.392      382821.094     1931268.017      382524.219
     1931387.809      382331.511     1931471.142      381979.948
#Sta/Elev= 30
       0 1519.94    29.4  1498.9    39.2 1493.57    49.1 1490.21    78.5 1485.51
   127.6 1481.08   176.6 1479.64   245.3 1480.64   323.8 1480.34   372.9 1478.02
     422 1478.43   490.6 1476.73   537.9 1477.36   575.7 1478.86   585.2 1477.51
   604.1 1471.48   613.5 1470.33   628.7 1473.46   641.9 1476.52   651.4 1477.19
   737.1 1475.47   873.8    1474   893.3  1474.4   903.1 1475.43   942.1 1482.83
     991  1489.8  1010.5 1492.31  1059.3 1496.71  1069.1 1498.04  1078.8 1500.24
#Mann= 3 , 0 , 0
       0      .1       0   604.1    .045       0   628.7      .1       0
#XS Ineff= 2 , 0
                          650.71          1477.1
Permanent Ineff=
       F       F
Bank Sta=604.1,628.7
XS Rating Curve= 0 ,0
Exp/Cntr=0.3,0.1

Chan Stop Cuts=-1
Use User Specified Reach Order=0
Composite Channel Slope=5